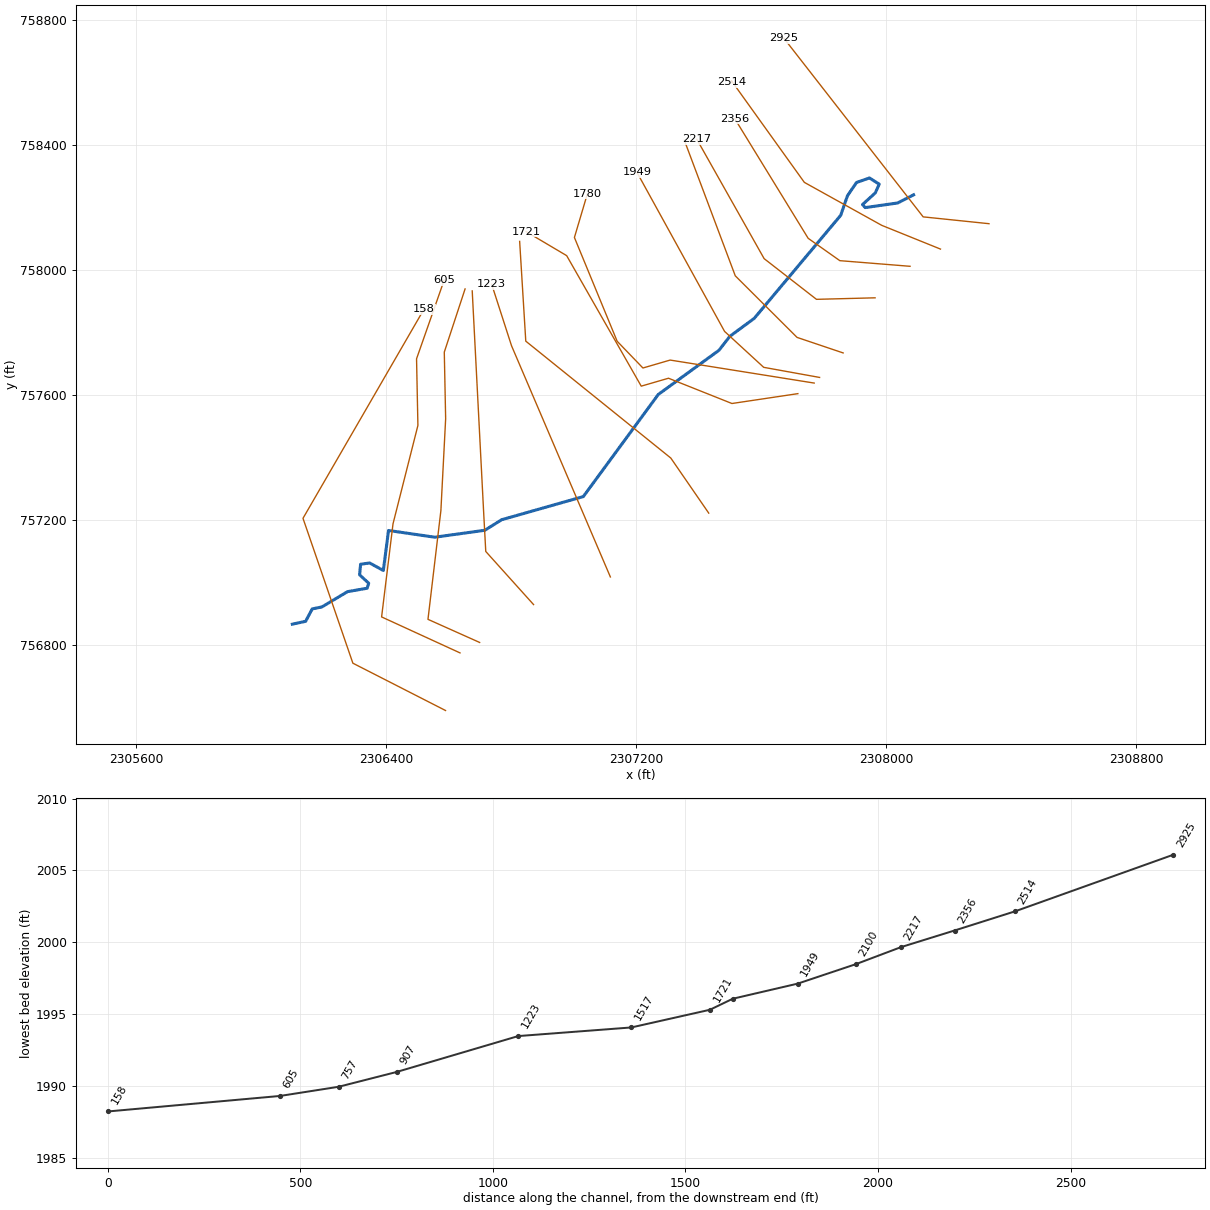
--- PONDLCKRN.prj (project) ---

Proj Title=PONDLCKRN
Current Plan=p01
Default Exp/Contr=0,0
English Units
Geom File=g01
Flow File=f01
Plan File=p01
BEGIN DESCRIPTION:
----------MODEL BY WOOD PLC 2022----------
AFH study
Randolph County, WV
HEC-RAS Version: RAS 6.2
Vertical Datum: NAVD88
Projection: NAD 1983 StatePlane West Virginia S FIPS 4702 (US Feet)
Terrain: 1-meter LIDAR (FEMA Region III 3DEP collected 2016-2018)
Land Use: 2019 NLCD
Hydrologic Method:
WV SIR2010-5033 regression equations
Additional Model Notes:
None
END DESCRIPTION:
DSS File=dss
DSS Export Rating Curves= 0
DSS Export Rating Curve Sorted= 0
DSS Export Volume Flow Curves= 0
DXF OffsetX= 0
DXF OffsetY= 0
DXF ScaleX= 0
DXF ScaleY= 0

--- PONDLCKRN.p01 (plan) ---

Plan Title=Floodplain
Program Version=6.20
Short Identifier=Floodplain
Geom File=g01
Flow File=f01
Subcritical Flow
K Sum by GR= 0
Std Step Tol= 0.01
Critical Tol= 0.01
Num of Std Step Trials= 20
Max Error Tol= 0.3
Flow Tol Ratio= 0.001
Split Flow NTrial= 30
Split Flow Tol= 0.02
Split Flow Ratio= 0.02
Log Output Level= 0
Friction Slope Method= 1
Unsteady Friction Slope Method= 2
Unsteady Bridges Friction Slope Method= 1
Parabolic Critical Depth
Global Vel Dist= 0 , 0 , 0
Global Log Level= 0
CheckData=True
Encroach Param=-1 ,0,0, 0
Computation Interval=0.1SEC
Output Interval=1SEC
Instantaneous Interval=Max Profile
Mapping Interval=1HOUR
Computation Time Step Use Courant=        0
Computation Time Step Use Time Series=    0
Computation Time Step Count To Double=0
Computation Time Step Max Doubling=0
Computation Time Step Max Halving=0
Computation Time Step Residence Courant=0
Run HTab= 0
Run UNet= 0
Run Sediment= 0
Run PostProcess= 0
Run WQNet= 0
Run RASMapper=-1
UNET Theta= 0
UNET Theta Warmup= 0
UNET ZTol= 0
UNET ZSATol= 0
UNET MxIter= 0
UNET Max Iter WO Improvement= 0
UNET MaxInSteps= 0
UNET DtIC= 0
UNET DtMin= 0
UNET MaxCRTS= 0
UNET WFStab= 0
UNET SFStab= 0
UNET WFX= 1
UNET SFX= 1
UNET Gravity=32.174
UNET 1D Methodology=Finite Difference
UNET DSS MLevel= 1
UNET Pardiso=0
UNET DZMax Abort= 0
UNET Use Existing IB Tables= 0
UNET Froude Reduction=False
UNET Froude Limit= 0
UNET Froude Power= 0
UNET D1 Cores= 0
UNET WindReference=Eulerian
UNET WindDragFormulation=Hsu (1988)
UNET D2 Coriolis=0
UNET D2 Cores= 0
UNET D2 Theta= 1
UNET D2 Theta Warmup= 1
UNET D2 Z Tol= 0.01
UNET D2 Volume Tol= 0.01
UNET D2 Max Iterations= 20
UNET D2 Equation= 0
UNET D2 RampUpFraction=0.1
UNET D2 TimeSlices= 1
UNET D2 Turbulence Formulation=Non-Conservative (original)
UNET D2 Eddy Viscosity=0.3
UNET D2 Transverse Eddy Viscosity=0.1
UNET D2 Smagorinsky Mixing=0
UNET D2 BCVolumeCheck=0
UNET D2 Cores=0
UNET D2 SolverType=PARDISO (Direct)
UNET D2 Minimum Iterations= 2147483647
UNET D2 Maximum Iterations= 2147483647
UNET D2 Restart Number= 10
UNET D2 Relaxation Coeff=1.3
UNET D2 SOR Precondition Iterations= 10
UNET D2 ILUT Maximum Fill= 8
UNET D2 ILUT Tolerance=1E-08
UNET D1D2 MaxIter= 0
UNET D1D2 ZTol=0.01
UNET D1D2 QTol=0.1
UNET D1D2 MinQTol=1
DSS File=dss
Write IC File= 0
Write IC File at Fixed DateTime=0
Write IC File at Sim End=0
Echo Input=False
Echo Parameters=False
Echo Output=False
Write Detailed= 0
HDF Write Warmup=0
HDF Write Time Slices=0
HDF Flush=0
HDF Compression= 1
HDF Chunk Size= 1
HDF Spatial Parts= 1
HDF Use Max Rows=0
HDF Fixed Rows= 1
Calibration Method= 0
Calibration Iterations= 20
Calibration Max Change=0.05
Calibration Tolerance=0.2
Calibration Maximum=1.5
Calibration Minimum=0.5
Calibration Optimization Method= 1
WQ AD Non Conservative
WQ ULTIMATE=-1
WQ Max Comp Step=1HOUR
WQ Output Interval=15MIN
WQ Output Selected Increments= 0
WQ Output face flow=0
WQ Output face velocity=0
WQ Output face area=0
WQ Output face dispersion=0
WQ Output cell volume=0
WQ Output cell surface area=0
WQ Output cell continuity=0
WQ Output cumulative cell continuity=0
WQ Output face conc=0
WQ Output face dconc_dx=0
WQ Output face courant=0
WQ Output face peclet=0
WQ Output face adv mass=0
WQ Output face disp mass=0
WQ Output cell mass=0
WQ Output cell source sink temp=0
WQ Output nsm pathways=0
WQ Output nsm derived pathways=0
WQ Create Restart=0
WQ Fixed Restart=0
WQ System Summary=0
WQ Write To DSS=0
Sorting and Armoring Iterations= 10
XS Update Threshold= 0.02
Bed Roughness Predictor= 0
Hydraulics Update Threshold= 0.02
Energy Slope Method= 1
Volume Change Method= 1
Sediment Retention Method= 0
Sediment TS Multiplier= 1
Warm Up Method= 0
XS Weighting Method= 0
Number of US Weighted Cross Sections= 1
Number of DS Weighted Cross Sections= 1
Upstream XS Weight=0
Main XS Weight=1
Downstream XS Weight=0
Number of DS XS's Weighted with US Boundary= 1
Upstream Boundary Weight= 1
Weight of XSs Associated with US Boundary= 0
Number of US XS's Weighted with DS Boundary= 1
Downstream Boundary Weight= 0.5
Weight of XSs Associated with DS Boundary= 0.5
Percentile Method= 0
Sediment Output Level= 3
Mass or Volume Output= 0
Output Increment Type= 1
Profile and TS Output Increment= 1
Transport Output Increment 1
XS Output Flag= 0
XS Output Increment= 10
Read HDF5 Sediment Hotstart= 0
Sediment Hotstart Type= 0
Write Gradation File= 0
Read Gradation Hotstart= 0
Write HDF5 File= 1
Write Binary Output= 1
Write DSS Sediment File= 0
DSS Sediment Output Type= 1
SV Curve= 0
Specific Gage Flag= 0
Subcell Erosion Methods= 0
Subcell Deposition Methods= 0
Advection Scheme= 1
Matrix Solver= 0
Implicit Weighting Factor= 1
Maximum Outer Loop Convergence Iterations= 5
Convergence Maximum Absolute= 0.001
Convergence RMSE= 0.0001
Grain Fractions Max Abs Error= 0.001
Max Subgrid Regions= 1
Max Subgrid Length Scale= 3.402823E+38
Initial Layer Thickness= 3.402823E+38
Min Layer Thickness= 3.402823E+38
Max Layer Thickness= 3.402823E+38
Number of Layers= 5

--- PONDLCKRN.f01 (steady flow) ---

Flow Title=Flow
Program Version=6.20
Number of Profiles= 1
Profile Names=P100yr
River Rch & RM=PONDLCKRN,Main            ,2925
     314
Boundary for River Rch & Prof#=PONDLCKRN,Main            , 1
Up Type= 0
Dn Type= 3
Dn Slope=0.0024
DSS Import GetInterval= 0
DSS Import GetPeak= 0
DSS Import FillOption= 0

--- PONDLCKRN.g01 (geometry) ---

Geom Title=Geometry
Program Version=6.20

River Reach=PONDLCKRN       ,Main
Reach XY= 30
     2308087.251      758240.528     2308036.209      758214.486
     2307932.476       758199.71     2307923.659      758209.295
     2307964.595      758246.674     2307977.148      758274.681
     2307945.952      758294.485     2307904.597      758280.059
     2307875.658      758237.839     2307853.926      758174.992
     2307577.199      757845.215     2307499.221      757787.854
     2307464.268      757742.987     2307270.153      757601.751
      2307030.28      757275.021      2306768.95      757200.931
     2306715.115      757167.194     2306554.763      757144.971
     2306406.977      757166.5252306390.23949218757038.432101026
2306346.52730773757062.601856186 2306317.4847977757058.446756223
2306314.35454357757024.583097903     2306343.476      756997.781
     2306338.486      756981.671     2306275.793       756970.84
     2306193.555       756921.792306162.86008566756915.637596033
2306141.59709357756875.894006068     2306099.051      756866.708

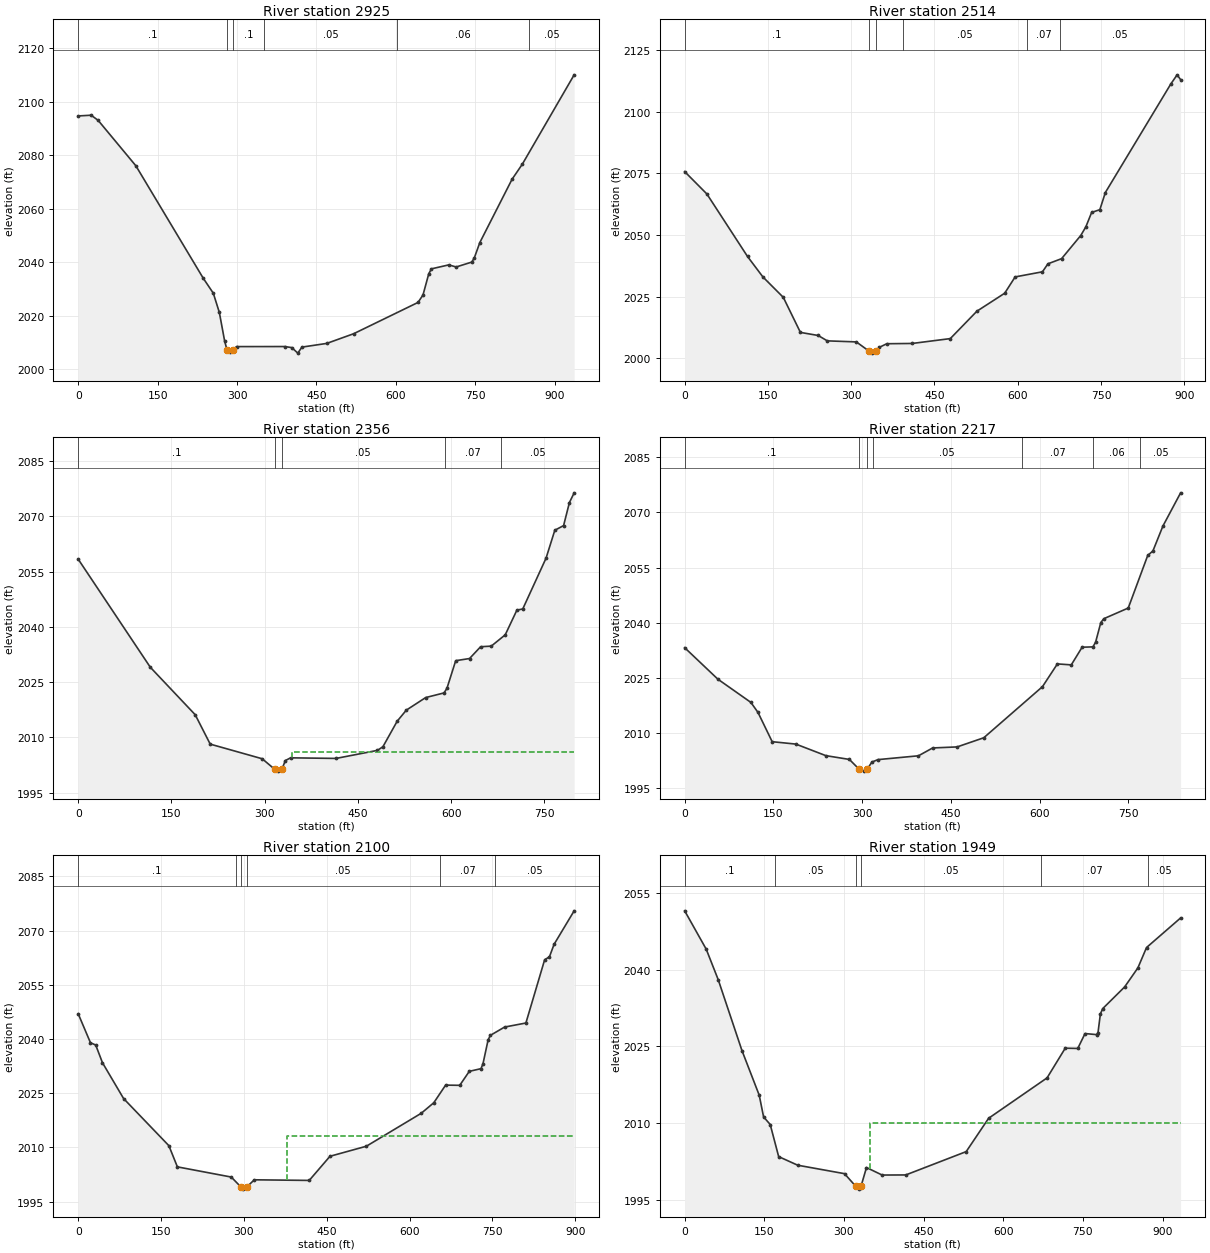
Type RM Length L Ch R = 1 ,2925    ,401.7,410.8,410.2
XS GIS Cut Line= 3
2308328.50771342758148.1569099892308117.81099736758169.997423239
2307672.00757985758741.704975953
#Sta/Elev= 30
       0 2094.71    24.5 2094.98    37.7 2093.05   108.9 2076.09   236.1  2034.1
   255.2 2028.48   266.6 2021.28   276.7  2010.5   281.32007.155   286.9 2006.36
   291.9 2007.16     299 2008.54   390.1 2008.56   403.4 2008.17   414.8  2006.1
   422.6 2008.35   469.5 2009.73   520.2 2013.34   641.9 2025.04   651.3 2027.83
   662.2 2035.78   667.3 2037.59   699.8 2039.06     714 2038.29   743.4 2040.11
   748.2 2041.67   758.6 2047.39   819.4 2071.02     839 2076.72   936.8 2110.07
#Mann= 6 ,-1,0
       0      .1       0   281.3    .045       0   291.9      .1       0
  351.83     .05       0  601.83     .06       0  851.83     .05       0
Bank Sta=281.3,291.9
XS Rating Curve= 0 ,0
Exp/Cntr(USF)=0,0
Exp/Cntr=0.3,0.1

Type RM Length L Ch R = 1 ,2514    ,158.7,157.8,157.4
XS GIS Cut Line= 5
2308173.22428129758066.917310838 2307985.1910239758142.915308998
2307737.52969829758280.4078200022307503.80476903758606.312768098
2307506.05698077 758600.46266063
#Sta/Elev= 30
       0 2075.73      40 2066.66   113.2 2041.33   140.8 2033.07   177.7 2024.75
   208.5 2010.56   240.5 2009.31   256.9 2007.13   309.2 2006.71   332.52002.913
   337.6 2002.16  345.16  2002.9   350.4 2004.48   364.1 2005.97   409.9 2006.08
   478.5 2008.05   526.4 2019.15   576.5 2026.44   595.3 2033.05   644.5 2035.12
   654.4 2038.36     679 2040.45   713.5 2049.83   722.7 2053.34   733.1 2059.18
   747.9  2060.3   757.8 2067.25   875.9  2111.3   887.1 2114.95   893.4    2113
#Mann= 6 ,-1,0
       0      .1       0   332.5    .045       0  345.16      .1       0
  392.81     .05       0  616.08     .07       0  676.08     .05       0
Bank Sta=332.5,345.16
XS Rating Curve= 0 ,0
Exp/Cntr(USF)=0,0
Exp/Cntr=0.3,0.1

Type RM Length L Ch R = 1 ,2356    ,139.4,139.3,138.9
XS GIS Cut Line= 4
 2308075.8759149758011.8549933692307851.11443425758029.878608769
2307749.75037598758101.4520526532307515.25924321758483.642785827
#Sta/Elev= 30
       0 2058.35     116 2029.02   188.3 2016.12   212.4 2008.15     296 2004.18
   316.1 2001.33   321.8 2000.82   327.8 2001.34   333.3 2003.69   341.7 2004.43
   414.9 2004.27   481.4 2006.45   490.3 2007.44   513.2 2014.36   527.9 2017.37
   559.1 2020.79   588.6 2022.05   593.3 2023.29   607.4  2030.8   629.7 2031.39
   647.5 2034.59   664.6 2034.75   687.1 2037.82   705.9 2044.54   715.3 2044.84
   752.8 2058.64   766.9 2066.22     781 2067.47   790.4 2073.74     798 2076.37
#Mann= 5 ,-1,0
       0      .1       0   316.1    .045       0   327.8     .05       0
  589.57     .07       0  679.57     .05       0
#XS Ineff= 2 , 0
                          343.24         2006.06
Permanent Ineff=
       F       F
Bank Sta=316.1,327.8
XS Rating Curve= 0 ,0
Exp/Cntr(USF)=0,0
Exp/Cntr=0.3,0.1

Type RM Length L Ch R = 1 ,2217    ,117.4,116.6,116
XS GIS Cut Line= 4
2307963.99257094757910.9857360722307776.32880033757906.135912727
2307608.80523066   758036.4102492307393.50081684758418.247673684
#Sta/Elev= 30
       0 2033.21    56.2 2024.64   111.9 2018.34   123.9 2015.62   147.9 2007.66
   187.9 2007.01   238.6 2003.87   278.4 2002.84   294.3 2000.28   303.5 1999.66
  308.87 2000.27   316.5 2002.13   326.8 2002.79   395.2 2003.83   419.2 2005.96
   460.5 2006.24   505.6 2008.73   604.8 2022.62     630  2028.8   653.5 2028.54
   671.8 2033.34   690.1 2033.43   694.6 2034.71   703.4 2040.04   708.5 2041.09
   749.8 2043.99   782.7 2058.28   791.5 2059.51   808.4 2066.28   838.3  2075.3
#Mann= 7 ,-1,0
       0      .1       0   294.3    .045       0  308.87      .1       0
  317.73     .05       0  569.94     .07       0  689.94     .06       0
  769.94     .05       0
Bank Sta=294.3,308.87
XS Rating Curve= 0 ,0
Exp/Cntr(USF)=0,0
Exp/Cntr=0.3,0.1

Type RM Length L Ch R = 1 ,2100    ,151,151.5,151.5
XS GIS Cut Line= 4
2307861.76690223757734.6112960232307714.19918988757784.353221532
2307516.51271471757981.3812262362307353.55038322758415.112765678
#Sta/Elev= 30
       0 2046.99    22.2 2038.98    31.7 2038.35    43.9 2033.46    82.2 2023.54
   164.2  2010.5   179.6 2004.64   277.2 2001.82  295.11 1999.01   299.2 1998.48
   304.8 1999.02     319 2001.06   418.4 2000.89     456 2007.57   521.9 2010.35
   621.3 2019.47     644 2022.38   665.4 2027.26     691  2027.2   708.3 2031.07
   729.5 2031.81   733.1 2033.18   742.4 2039.79   746.5 2041.03   772.2 2043.32
   810.8 2044.44   844.8 2061.96   853.4 2062.74   861.9 2066.23   898.2 2075.48
#Mann= 6 ,-1,0
       0      .1       0  285.73     .05       0  295.11    .045       0
   304.8     .05       0  654.83     .07       0  754.83     .05       0
#XS Ineff= 2 , 0
                          378.19         2013.11
Permanent Ineff=
       F       F
Bank Sta=295.11,304.8
XS Rating Curve= 0 ,0
Exp/Cntr(USF)=0,0
Exp/Cntr=0.3,0.1

Type RM Length L Ch R = 1 ,1949    ,165.4,168.4,170.2
BEGIN DESCRIPTION:
Structure XS 4
END DESCRIPTION:
XS GIS Cut Line= 4
 2307786.3854783757656.2328844342307607.48781231757688.568082986
2307482.30436316757803.507480414 2307201.3370594758313.480921727
#Sta/Elev= 30
       0 2051.48    40.6 2043.98    63.2 2038.02   107.9 2024.18   140.4 2015.46
   148.6 2011.23   161.1 2009.74     177 2003.47   212.9 2001.79     301 2000.14
   322.1 1997.68   327.5 1997.12  332.06 1997.67   342.4 2001.34   371.9 1999.87
   416.4 1999.89   530.2 2004.45   572.4 2010.96   682.5 2018.85   716.7 2024.65
   740.3  2024.6     754 2027.51   775.6  2027.3   778.4 2027.67   782.9 2031.34
   787.2 2032.37   828.6 2036.62   853.5 2040.33   869.8 2044.31     934 2050.09
#Mann= 6 ,-1,0
       0      .1       0     170     .05       0   322.1    .045       0
  332.06     .05       0  671.74     .07       0  871.74     .05       0
#XS Ineff= 2 , 0
                           348.3         2010.03
Permanent Ineff=
       F       F
Bank Sta=322.1,332.06
XS Rating Curve= 0 ,0
Exp/Cntr(USF)=0,0
Exp/Cntr=0.3,0.1

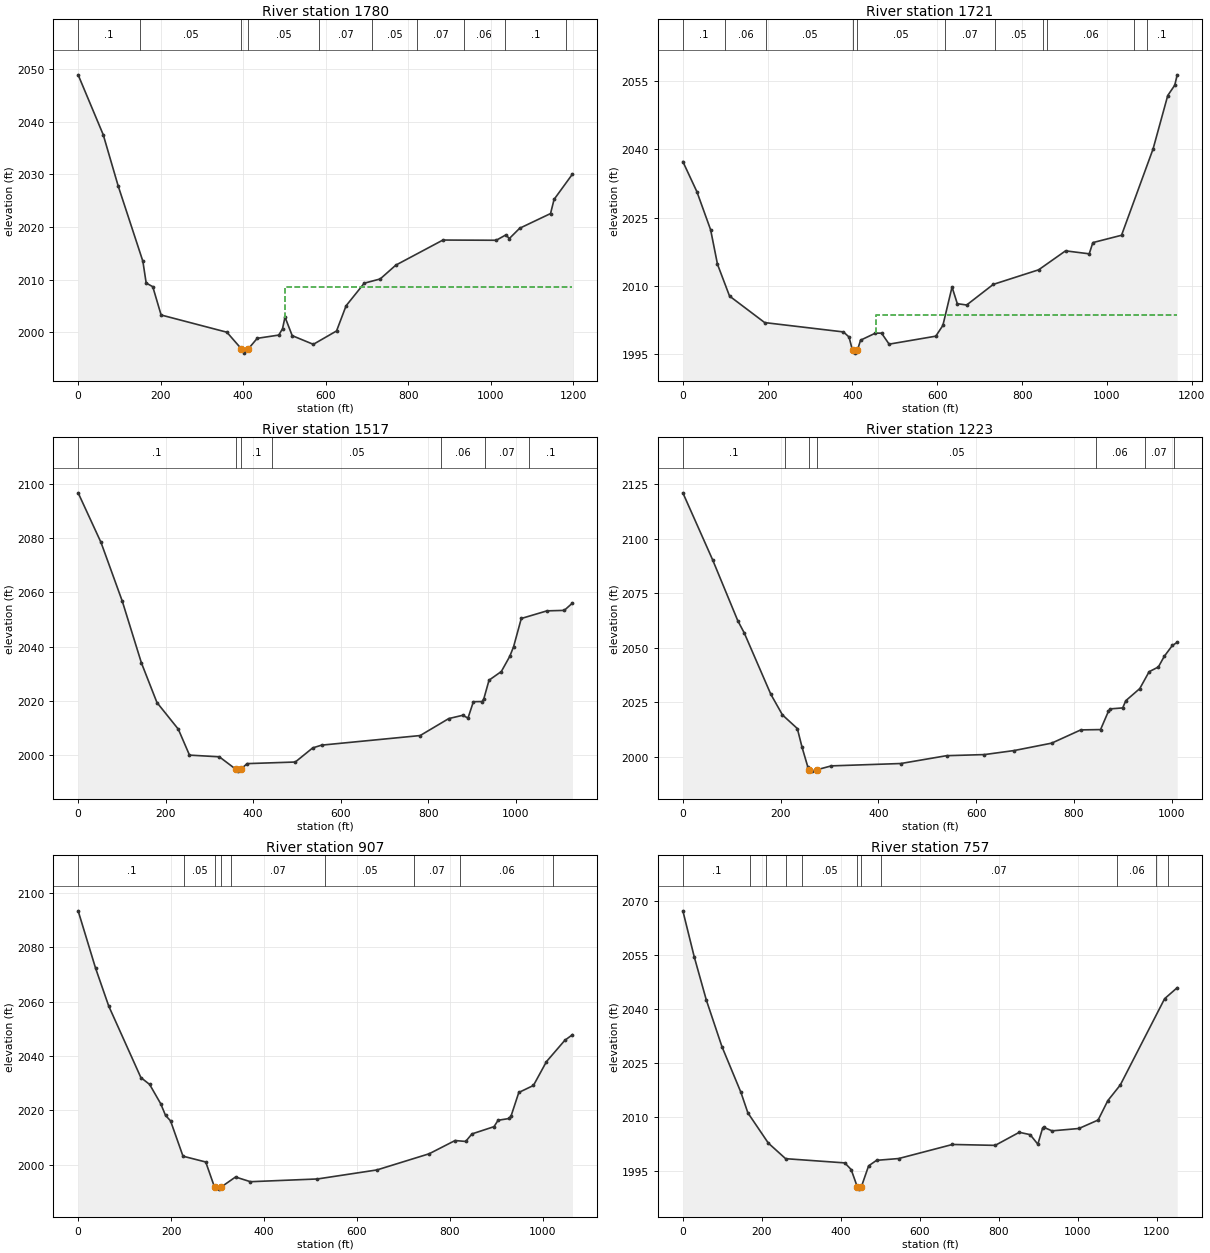
Type RM Length L Ch R = 1 ,1780    ,59.3,59.6,58
BEGIN DESCRIPTION:
Structure XS 3
END DESCRIPTION:
XS GIS Cut Line= 6
2307769.10234949757638.1986358932307308.21931265757711.798781515
2307220.98414717757686.4212788282307138.50726344757772.070350396
2307001.76111481758104.0341595152307043.33809963758243.932408795
#Sta/Elev= 30
       0 2048.91    60.9 2037.52    96.9 2027.85   156.9 2013.51   164.9 2009.38
   180.9 2008.68   201.1 2003.31   360.5 2000.04   395.8 1996.87   402.6 1996.07
  412.15 1996.85     434 1998.88   486.4  1999.5   495.4 2000.72   501.4 2002.92
   518.8 1999.39     570 1997.74   626.3 2000.28   649.4 2005.06   693.4 2009.35
     732 2010.15     770 2012.78   884.1 2017.54  1013.3  2017.5  1036.5 2018.51
  1045.1 2017.83  1070.1 2019.78  1144.9 2022.57  1153.5 2025.26  1198.1 2030.07
#Mann= 10 ,-1,0
       0      .1       0     150     .05       0   395.8    .045       0
  412.15     .05       0  583.27     .07       0  712.17     .05       0
  822.17     .07       0  933.98     .06       0 1033.98      .1       0
 1182.19     .05       0
#XS Ineff= 2 , 0
                          500.79         2008.62
Permanent Ineff=
       F       F
Bank Sta=395.8,412.15
XS Rating Curve= 0 ,0
Exp/Cntr(USF)=0,0
Exp/Cntr=0.3,0.1

Type RM Length L Ch R = 1 ,1721    ,206.1,203.9,203.5
BEGIN DESCRIPTION:
Structure XS 2
END DESCRIPTION:
XS GIS Cut Line= 6
2307716.82689992757604.358932706 2307505.8441766757572.819861604
 2307302.8241551757653.7106514182307215.58898962757628.333148731
2306976.96721574758045.946029419 2306847.1886504758122.798368733
#Sta/Elev= 30
       0 2037.33    33.1 2030.72    65.5 2022.36    81.7 2014.79   110.1 2007.82
     193    2002   378.8 1999.95   391.9 1998.83   400.1 1995.88   406.3  1995.3
  411.42 1995.88   419.1 1998.14   454.2 1999.69   468.6 1999.68   486.4 1997.27
   596.5 1999.02   613.2 2001.38   634.8  2009.8   647.2 2006.15   669.3 2005.86
     732 2010.38     839 2013.58   902.5 2017.74   958.3 2017.09   966.9 2019.55
  1034.5 2021.16  1108.9  2040.1  1143.5 2051.82    1160 2054.08  1165.8 2056.36
#Mann= 11 ,-1,0
       0      .1       0     100     .06       0  196.64     .05       0
   400.1    .045       0  411.42     .05       0  618.16     .07       0
  737.06     .05       0  848.57     .07       0  858.57     .06       0
 1064.99     .05       0 1094.99      .1       0
#XS Ineff= 2 , 0
                          456.59         2003.64
Permanent Ineff=
       F       F
Bank Sta=400.1,411.42
XS Rating Curve= 0 ,0
Exp/Cntr(USF)=0,0
Exp/Cntr=0.3,0.1

Type RM Length L Ch R = 1 ,1517    ,298.6,293.7,290.8
BEGIN DESCRIPTION:
Structure XS 1
END DESCRIPTION:
XS GIS Cut Line= 4
2307431.60438211 757222.089595942307310.19966246757398.322253486
2306846.12033092757772.3271156132306826.53892453758091.504039837
#Sta/Elev= 30
       0 2096.77    52.3 2078.45   100.9 2056.78   144.6 2034.02   180.1 2019.39
   228.9 2009.56   254.5 1999.98   322.7 1999.35   359.7 1994.85   365.4 1994.07
  372.34 1994.85   386.1 1996.84   496.3 1997.43   536.1 2002.64   556.4 2003.66
   781.7  2007.2     847 2013.46     879 2014.68     891 2013.64   903.3 2019.69
   923.1 2019.75   927.1 2020.72   939.1 2027.63   967.2 2030.83   986.4 2036.41
   995.2 2039.98  1012.8  2050.4  1071.4 2053.21    1111 2053.39  1129.8  2056.1
#Mann= 7 ,-1,0
       0      .1       0   359.7    .045       0  372.34      .1       0
     444     .05       0  830.03     .06       0  930.03     .07       0
 1030.03      .1       0
Bank Sta=359.7,372.34
XS Rating Curve= 0 ,0
Exp/Cntr(USF)=0,0
Exp/Cntr=0.3,0.1

Type RM Length L Ch R = 1 ,1223    ,317.4,315.8,312.1
XS GIS Cut Line= 3
2307116.84446661 757017.798396952306800.49105587757757.690749047
2306737.01224648757954.370994541
#Sta/Elev= 30
       0 2121.13      61 2090.35   112.4 2062.46   125.5 2056.92   179.9 2028.77
   203.8 2019.24   234.2 2013.01   243.8 2004.49   255.9 1995.21  258.58  1994.1
   264.7 1993.47   274.3 1994.11   303.8 1995.88   445.9 1996.96   539.4 2000.55
   617.1 2001.06     678 2002.92   754.6 2006.31   814.1 2012.38   854.6 2012.53
   870.8 2020.97   874.4 2022.02   899.9 2022.47   906.2 2025.78   934.8 2031.33
   953.9 2039.06   972.9 2041.26   984.9 2046.11  1001.5 2051.12  1011.4 2052.54
#Mann= 7 ,-1,0
       0      .1       0     210     .05       0  258.58    .045       0
   274.3     .05       0  844.69     .06       0  944.69     .07       0
 1004.69      .1       0
Bank Sta=258.58,274.3
XS Rating Curve= 0 ,0
Exp/Cntr(USF)=0,0
Exp/Cntr=0.3,0.1

Type RM Length L Ch R = 1 ,907     ,151.3,150.5,150.2
BEGIN DESCRIPTION:
Structure XS 4
END DESCRIPTION:
XS GIS Cut Line= 4
2306871.06030491756929.4058908262306718.07266729757099.384276562
2306711.94418587 757212.661188122306674.74275915  757933.0966888
#Sta/Elev= 30
       0 2093.36    37.4 2072.32    65.8 2058.33     135 2032.01   153.8 2029.49
   177.7 2022.37     188  2018.1   198.8 2016.09   225.6 2003.09   274.5 2000.95
  293.42  1991.7   302.6 1990.97  307.55 1991.72   338.6 1995.43   370.7  1993.7
   514.9 1994.71   642.8 1998.03   755.2 2003.98   810.9 2008.85   833.7 2008.51
   847.3 2011.29   894.7 2013.95   903.4  2016.3   927.4 2016.96   931.4 2017.89
     948 2026.53   979.5 2029.11  1007.5 2037.88    1047 2045.72  1063.5 2047.79
#Mann= 9 ,-1,0
       0      .1       0  228.69     .05       0  293.42    .045       0
  307.55     .05       0  328.69     .07       0  532.13     .05       0
  722.13     .07       0  822.13     .06       0 1022.13      .1       0
Bank Sta=293.42,307.55
XS Rating Curve= 0 ,0
Exp/Cntr(USF)=0,0
Exp/Cntr=0.3,0.1

Type RM Length L Ch R = 1 ,757     ,152.5,152.4,151.8
BEGIN DESCRIPTION:
Structure XS 3
END DESCRIPTION:
XS GIS Cut Line= 6
2306698.49642491756808.2181770452306533.14232647756882.192378978
2306574.48085108757230.3062704292306589.71083383 757524.02736634
2306585.35941019757737.247124853 2306651.8742269757939.408367738
#Sta/Elev= 30
       0 2067.27    28.8  2054.5    59.5 2042.47    98.9 2029.57   147.2 2016.79
   164.7 2011.13   216.5 2002.73   260.3  1998.4   410.2 1997.23   426.3 1995.38
  441.73 1990.61   446.4 1989.94  452.11 1990.59   470.5 1996.41   490.6 1997.94
   546.7 1998.44   682.9 2002.35   791.1  2002.1   852.1 2005.73   879.6 2005.08
   899.1 2002.42   911.1 2006.85   915.1 2007.07   935.1 2006.13  1003.2 2006.79
  1051.8 2009.14  1076.3 2014.52  1107.9 2018.87  1220.2 2042.85  1252.1 2045.91
#Mann= 11 ,-1,0
       0      .1       0     170     .07       0  211.15     .08       0
  261.15      .1       0  301.15     .05       0  441.73    .045       0
  452.11     .05       0  501.77     .07       0 1099.23     .06       0
 1199.23     .07       0 1229.23      .1       0
Bank Sta=441.73,452.11
XS Rating Curve= 0 ,0
Exp/Cntr(USF)=0,0
Exp/Cntr=0.3,0.1

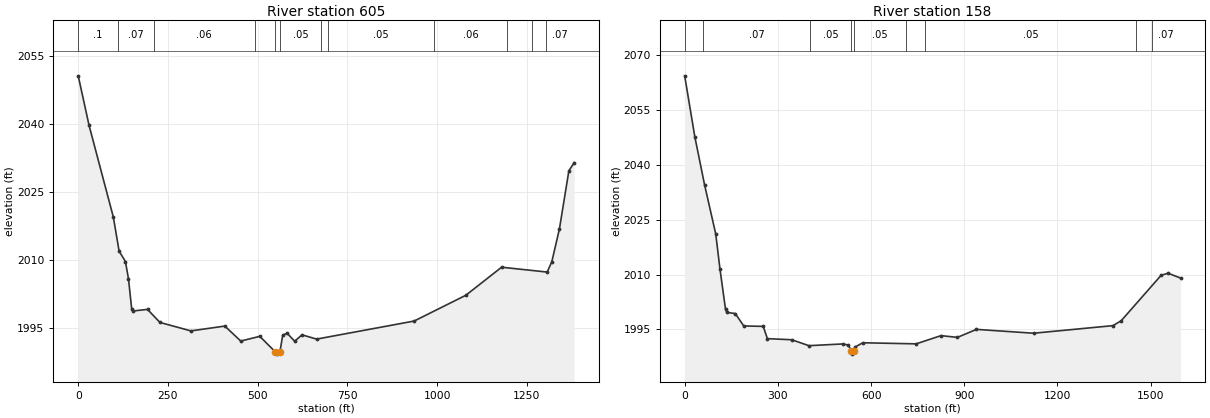
Type RM Length L Ch R = 1 ,605     ,436.2,447,446.3
BEGIN DESCRIPTION:
Structure XS 2
END DESCRIPTION:
XS GIS Cut Line= 6
2306635.66043114 756774.817245422306384.76011219756889.918356224
2306421.32325336757188.0754583772306500.93002115757502.600966522
2306496.57859751757715.8207250352306585.04672253757967.875850451
#Sta/Elev= 30
       0 2050.62    30.2 2039.71    97.9 2019.49   113.9 2012.01   131.5  2009.7
     140 2005.94   149.1  1999.2   152.2  1998.8   193.1 1999.16   227.7 1996.28
     314 1994.42   408.5 1995.48   452.9 1992.18   505.9 1993.22     549 1989.81
   553.6  1989.3  562.04 1989.82   569.8 1993.47   582.1 1993.91     603 1992.14
   623.6 1993.55   664.2 1992.61     936 1996.59    1080 2002.27  1179.7 2008.45
  1306.7 2007.38  1319.6 2009.67  1340.8  2016.9  1367.1  2029.7  1381.8 2031.48
#Mann= 12 ,-1,0
       0      .1       0     110     .07       0     210     .06       0
  491.94     .05       0     549    .045       0  562.04     .05       0
  676.83     .07       0  696.83     .05       0  991.37     .06       0
 1194.63     .07       0 1264.63     .06       0 1304.63     .07       0
Bank Sta=549,562.04
XS Rating Curve= 0 ,0
Exp/Cntr(USF)=0,0
Exp/Cntr=0.3,0.1

Type RM Length L Ch R = 1 ,158     ,,,
BEGIN DESCRIPTION:
Structure XS 1
END DESCRIPTION:
XS GIS Cut Line= 4
2306589.28997638756590.5041606862306292.80015769756741.899493477
2306133.21669125757205.4620952992306520.45526037757874.685489937
#Sta/Elev= 30
       0 2064.35    32.7 2047.66    64.1 2034.51   100.1 2021.03   113.5 2011.55
   131.5 2000.47     136 1999.64   162.9 1999.32   190.1 1995.93   252.8 1995.81
   266.2 1992.46   344.8 1992.15   399.8 1990.53   509.8 1991.01   526.7 1990.68
   536.81989.048   539.4 1988.22  544.92 1989.06   547.9 1990.13   573.3 1991.33
   745.1 1991.03   825.1 1993.28   877.8  1992.8   939.3 1994.99  1123.2 1993.94
  1378.4 1996.01  1405.1 1997.35  1533.6 2009.78  1555.9 2010.35  1596.4 2009.02
#Mann= 9 ,-1,0
       0      .1       0      60     .07       0  402.91     .05       0
   536.8    .045       0  544.92     .05       0  712.91     .06       0
  772.91     .05       0 1453.17     .06       0 1503.17     .07       0
Bank Sta=536.8,544.92
XS Rating Curve= 0 ,0
Exp/Cntr(USF)=0,0
Exp/Cntr=0.3,0.1
LCMann Table=0

Chan Stop Cuts=-1
Use User Specified Reach Order=0
Composite Channel Slope=5